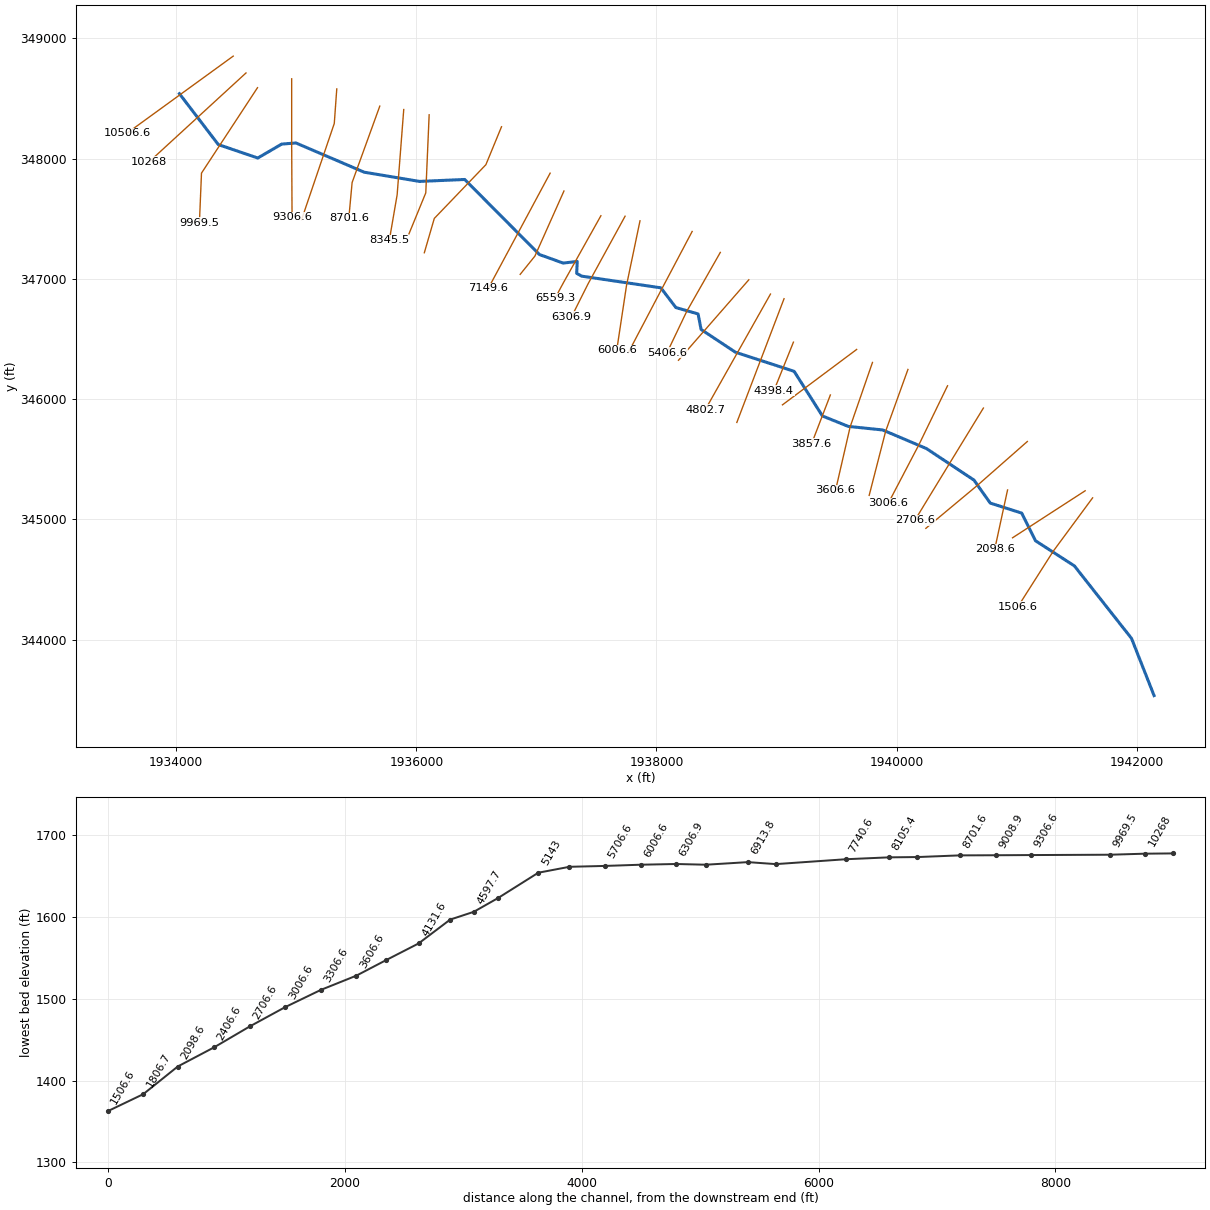
--- MeadowFork.prj (project) ---

Proj Title=MeadowFork
Current Plan=p01
Default Exp/Contr=0,0
English Units
Geom File=g01
Flow File=f01
Plan File=p01
BEGIN DESCRIPTION:
END DESCRIPTION:
DSS Export Rating Curves= 0
DSS Export Rating Curve Sorted= 0
DSS Export Volume Flow Curves= 0
DXF OffsetX= 0
DXF OffsetY= 0
DXF ScaleX= 0
DXF ScaleY= 0

--- MeadowFork.p01 (plan) ---

Plan Title=Floodplain
Program Version=4.00
Geom File=g01
Flow File=f01
K Sum by GR=0
Std Step Tol=0.01
Critical Tol=0.01
Num of Std Step Trials=20
Max Error Tol=0.3
Flow Tol Ratio=0.001
Split Flow NTrial=30
Split Flow Tol=0.02
Split Flow Ratio=0.02
Log Output Level=0
Friction Slope Method=1
Unsteady Friction Slope Method=2
Unsteady Bridges Friction Slope Method=1
Global Log Level=0
CheckData=False
Run HTab=0
Run UNet=0
Run PostProcess=0
UNET Theta=0
UNET Theta Warmup=0
UNET ZTol=0
UNET ZSATol=0
UNET MxIter=0
UNET MaxInSteps=0
UNET DtIC=0
UNET DtMin=0
UNET MaxCRTS=0
UNET WFStab=0
UNET SFStab=0
UNET WFX=0
UNET SFX=0
UNET DSS MLevel=0
UNET DZMax Abort=0
UNET Convert EG Bridges=0
UNET Use Existing IB Tables=0
UNET Froude Limit=0
UNET Froude Power=0
Write IC File=0
Echo Input=False
Echo Output=False
Write Detailed=0

--- MeadowFork.f01 (steady flow) ---

Flow Title=NFF Regression Equation
Program Version=4.00
Number of Profiles=1
Profile Names=P100yr
River Rch & RM=MeadowFork,Main      ,10506.6
519.2777
River Rch & RM=MeadowFork,Main      ,9306.6
523.3649
River Rch & RM=MeadowFork,Main      ,9008.9
580.7936
River Rch & RM=MeadowFork,Main      ,7149.6
623.0125
River Rch & RM=MeadowFork,Main      ,6559.3
725.5998
River Rch & RM=MeadowFork,Main      ,5143
764.3048
River Rch & RM=MeadowFork,Main      ,3306.6
830.1684
River Rch & RM=MeadowFork,Main      ,234.8
899.9935
Boundary for River Rch & Prof#=MeadowFork,Main      ,1
Up Type=0
Dn Type=3
Dn Slope=0.115985

--- MeadowFork.g01 (geometry) ---

Geom Title=USGS 3m DEM
Program Version=4.10

River Reach=MeadowFork      ,Main
Reach XY= 30
     1934026.158      348539.384     1934350.027      348116.557
     1934678.936      348004.662     1934878.574      348120.489
     1934996.644      348129.662     1935566.089      347886.606
     1936026.158      347810.218     1936402.726      347826.195
     1937024.422      347202.579     1937222.339      347131.398
     1937339.867      347144.816     1937335.186      347046.329
     1937376.587      347022.797     1938036.228      346925.597
     1938161.575      346761.606     1938346.354      346708.443
     1938371.644      346579.314     1938658.103      346390.079
     1939146.389      346231.653     1939382.061      345860.565
     1939597.339      345773.759     1939883.797      345744.245
     1940248.381      345589.731     1940644.214      345327.578
      1940779.63      345136.606     1941042.349       345052.99
      1941156.64      344823.429      1941481.02      344614.037
     1941956.714      344011.606     1942144.514      343536.307

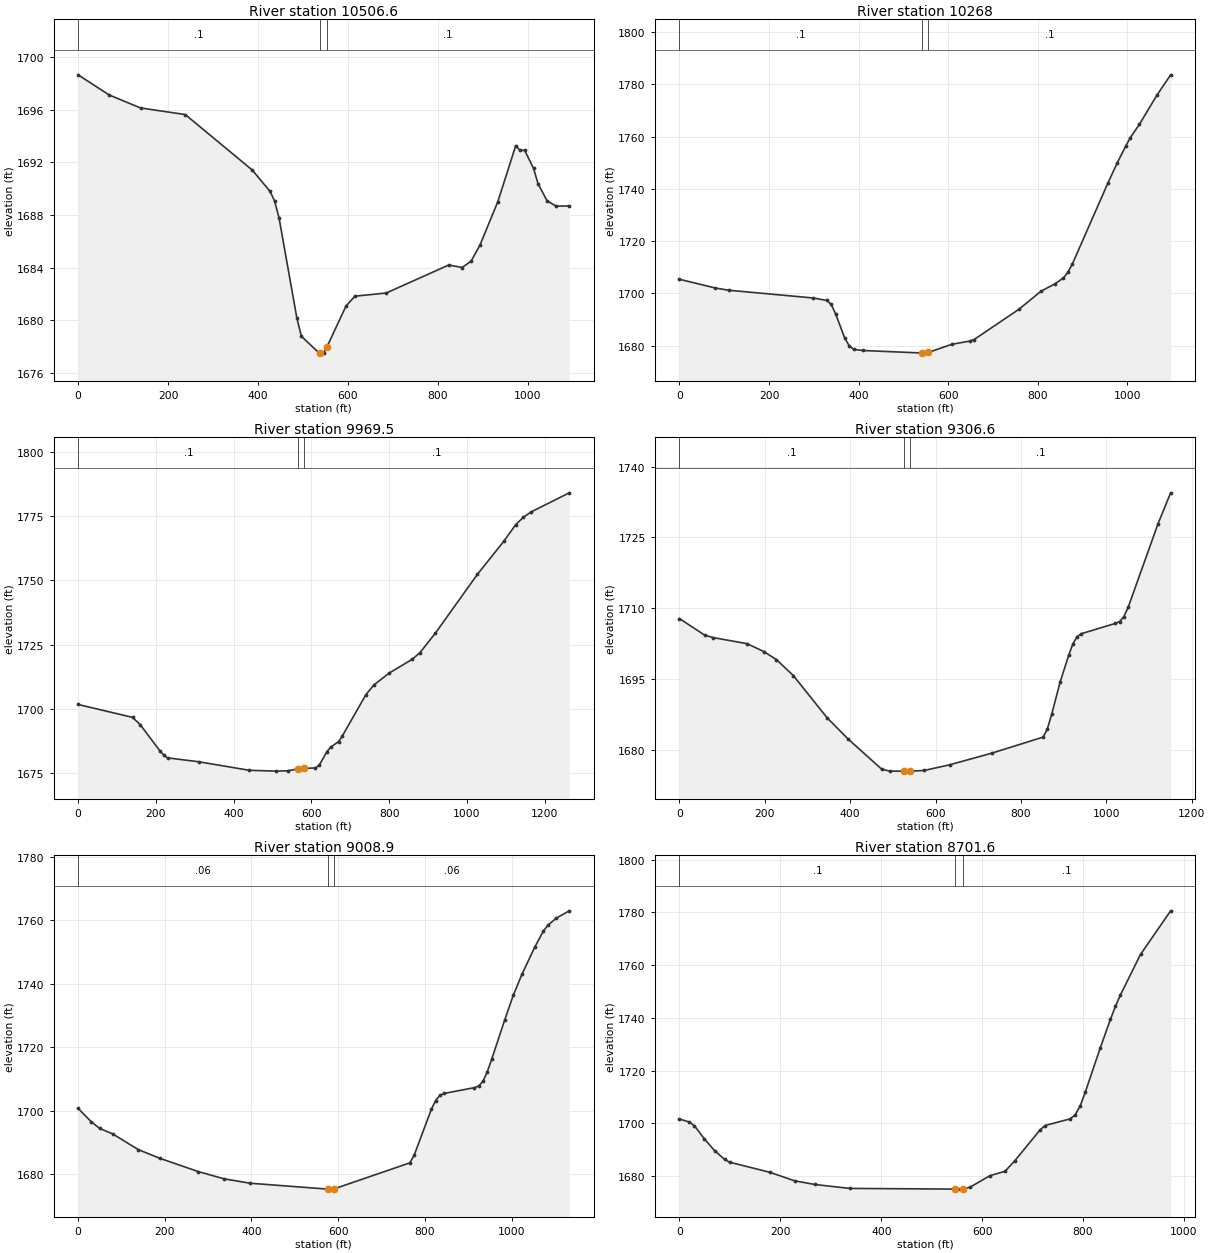
Type RM Length L Ch R = 1 ,10506.6 ,236,238.6,241.2
XS GIS Cut Line= 3
     1934474.253      348851.518     1934032.024      348531.285
     1933589.794      348211.051
#Sta/Elev= 30
       0 1698.66    69.5 1697.12     139 1696.14   238.2 1695.64   387.2 1691.42
   426.9 1689.79   436.8 1689.07   446.7 1687.79   486.4 1680.16   496.4 1678.78
   536.1  1677.5   538.5 1677.51     546 1677.53   553.5 1677.99   595.6 1681.08
   615.5 1681.83     685 1682.07     824  1684.2   853.8 1684.01   873.6 1684.49
   893.4 1685.71   933.2 1689.02   972.9 1693.27   982.8 1692.91   992.7 1692.93
  1012.6 1691.54  1022.5 1690.39  1042.4 1689.09  1062.2 1688.68    1092 1688.69
#Mann= 3 , 0 , 0
       0      .1       0   538.5    .045       0   553.5      .1       0
Bank Sta=538.5,553.5
XS Rating Curve= 0 ,0
Exp/Cntr=0.3,0.1

Type RM Length L Ch R = 1 ,10268   ,292.7,298.3,304
XS GIS Cut Line= 2
       1934580.8      348711.629     1933771.996      347971.171
#Sta/Elev= 30
       0 1705.43    79.8 1702.09   109.7 1701.24   299.1 1698.26     329 1697.32
   338.9 1695.81   348.9 1692.08   368.8 1683.02   378.8    1680   388.8 1678.61
   408.7 1678.18   540.9 1677.22   548.3 1677.17   555.9 1677.44   608.1 1680.55
     648 1681.78   657.9 1682.38   757.6 1693.91   807.5  1700.9   837.4 1703.58
   857.3 1705.93   867.3 1708.07   877.2 1711.28     957 1742.42   976.9 1749.77
   996.9 1756.58  1006.8 1759.64  1026.8 1764.68  1066.6 1776.02  1096.6 1783.64
#Mann= 3 , 0 , 0
       0      .1       0   540.9    .045       0   555.9      .1       0
Bank Sta=540.9,555.9
XS Rating Curve= 0 ,0
Exp/Cntr=0.3,0.1

Type RM Length L Ch R = 1 ,9969.5  ,649.4,662.8,676.2
XS GIS Cut Line= 3
      1934676.73      348589.361     1934210.117      347879.073
     1934192.835      347466.035
#Sta/Elev= 30
       0 1701.78     140 1696.78     160 1693.88     210 1683.86     220 1682.16
     230 1681.04   309.9 1679.54   439.9 1676.22   509.9 1675.89   539.9 1676.03
   566.6 1676.81   581.6 1676.95   609.9 1677.13   619.9 1678.12   639.9 1683.46
   649.9 1685.25   669.9 1687.37   679.9 1689.65   739.9 1705.53   759.9 1709.26
   799.8 1713.96   859.7 1719.38   879.4 1721.95   918.7 1729.47    1027 1752.36
  1095.9  1765.4  1125.4 1771.66  1145.1 1774.51  1164.8 1776.57  1263.2 1784.01
#Mann= 3 , 0 , 0
       0      .1       0   566.6    .045       0   581.6      .1       0
Bank Sta=566.6,581.6
XS Rating Curve= 0 ,0
Exp/Cntr=0.3,0.1

Type RM Length L Ch R = 1 ,9306.6  ,304.3,297.7,291
XS GIS Cut Line= 3
     1934961.246      348663.101     1934961.246      348129.662
     1934964.419      347512.492
#Sta/Elev= 30
       0  1707.8    59.3 1704.28      79 1703.77   158.1 1702.49   197.6 1700.82
   227.2  1699.1   266.7 1695.73   345.8 1686.79   395.1 1682.28   474.2 1675.85
   493.9 1675.48   525.9 1675.48   540.9 1675.48   573.3 1675.62     633 1676.82
   732.5 1679.31     852 1682.69   861.9 1684.45   871.9 1687.51   891.8 1694.36
   911.7 1700.01   921.7 1702.46   931.6    1704   941.6  1704.6  1021.2 1706.78
  1031.2 1707.17  1041.1 1708.22  1051.1 1710.18  1120.8 1727.83  1150.6 1734.44
#Mann= 3 , 0 , 0
       0      .1       0   525.9    .045       0   540.9      .1       0
Bank Sta=525.9,540.9
XS Rating Curve= 0 ,0
Exp/Cntr=0.3,0.1

Type RM Length L Ch R = 1 ,9008.9  ,307.9,307,306
XS GIS Cut Line= 3
       1935336.9      348578.992     1935316.162      348292.112
     1935043.518      347491.667
#Sta/Elev= 30
       0 1700.72    29.8 1696.58    49.6 1694.41    79.4 1692.71   138.9 1687.72
   188.4 1684.99   277.7 1680.77   337.4 1678.49   397.1 1677.12     576 1675.26
     591 1675.36   765.2 1683.54   775.1 1685.87   814.9 1700.41   824.8 1703.21
   834.8 1704.83   844.7 1705.45   914.4 1707.27   924.3 1707.81   934.3 1709.32
   944.2 1712.33   954.2 1716.21     984 1728.53  1003.9 1736.36  1023.8 1742.95
  1053.6  1751.6  1073.5 1756.64  1083.5 1758.43  1103.4 1760.75  1133.2 1763.03
#Mann= 3 , 0 , 0
       0     .06       0     576    .045       0     591     .06       0
Bank Sta=576,591
XS Rating Curve= 0 ,0
Exp/Cntr=0.3,0.1

Type RM Length L Ch R = 1 ,8701.6  ,350.1,356,361.9
XS GIS Cut Line= 3
     1935695.158      348435.838     1935464.786      347801.304
     1935437.135      347504.055
#Sta/Elev= 30
       0 1701.67    19.8 1700.49    29.8 1699.07    49.6 1694.08    69.5 1689.71
    89.4 1686.38    99.3  1685.3   178.7 1681.49   228.3 1678.24     268 1676.86
   337.5 1675.36     547  1675.1   555.9 1675.09     562 1675.18   575.8  1675.8
   615.5 1680.19   645.3 1681.85   665.1 1685.93   714.9 1697.55   724.8  1699.2
   774.6 1701.73   784.5 1703.27   794.5 1706.69   804.4 1711.82   834.3 1728.72
   854.2  1739.4   864.1 1744.34   874.1  1748.7   913.9 1764.03   973.6 1780.55
#Mann= 3 , 0 , 0
       0      .1       0     547    .045       0     562      .1       0
Bank Sta=547,562
XS Rating Curve= 0 ,0
Exp/Cntr=0.3,0.1

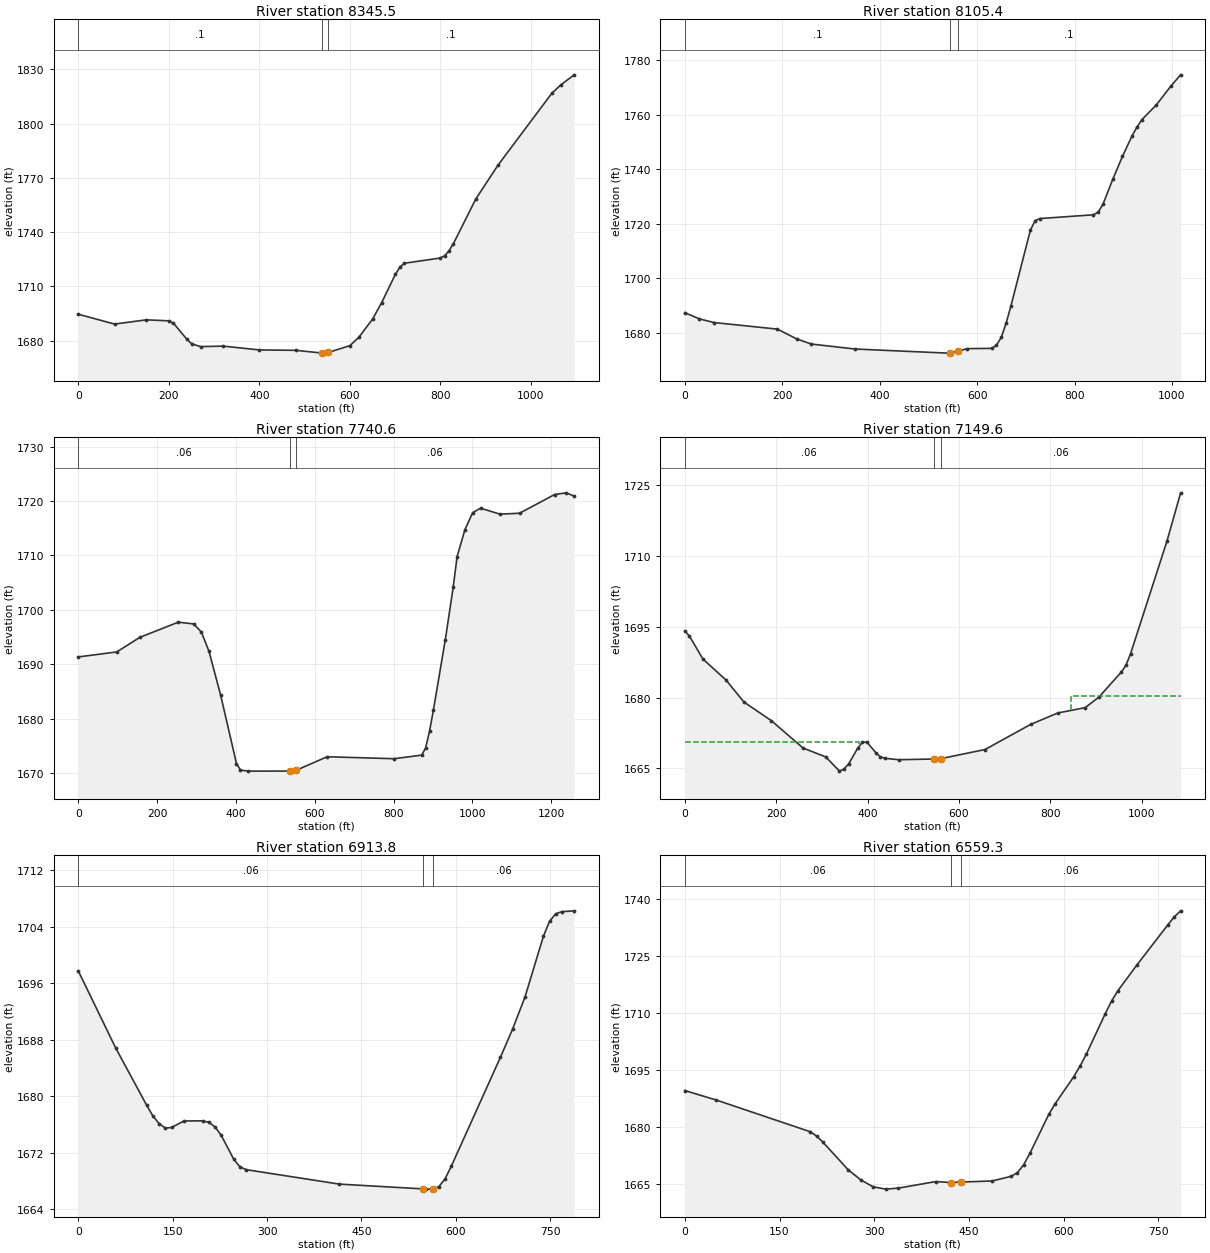
Type RM Length L Ch R = 1 ,8345.5  ,239.3,240,240.8
XS GIS Cut Line= 3
     1935894.725      348407.724     1935839.804      347699.341
     1935774.539      347319.648
#Sta/Elev= 30
       0 1694.55    80.1 1689.11   150.1 1691.45   200.1 1690.91   210.2 1689.64
   240.2 1680.61   250.2 1678.28   270.2 1676.64   320.2 1676.93   400.3 1674.81
   480.3  1674.6   537.5 1673.13   540.4 1673.05   552.5 1673.42   600.4 1677.22
   620.4 1681.94   650.5 1691.95   670.5 1701.02   700.5 1716.53   710.5 1720.52
   720.4 1722.74   799.4 1725.62   809.3 1726.84   819.2 1729.65     829 1733.63
   878.4 1758.28   927.8 1777.08  1046.4 1816.71  1066.1 1821.32  1095.8 1826.93
#Mann= 3 , 0 , 0
       0      .1       0   537.5    .045       0   552.5      .1       0
Bank Sta=537.5,552.5
XS Rating Curve= 0 ,0
Exp/Cntr=0.3,0.1

Type RM Length L Ch R = 1 ,8105.4  ,381.2,364.8,348.4
XS GIS Cut Line= 3
     1936106.402      348363.894     1936078.295      347714.895
     1935938.312       347374.44
#Sta/Elev= 30
       0 1687.49      30 1685.22      60 1683.88   189.9 1681.48   229.9 1677.88
   259.8 1676.01   349.8 1674.19   539.7 1672.69   545.2 1672.79   560.2 1673.42
   579.6 1674.33   629.6 1674.43   639.6 1675.56   649.6 1678.44   659.6 1683.69
   669.5 1690.01   709.3 1717.65   719.2 1721.21   729.2 1721.94   838.6  1723.3
   848.6  1724.3   858.5 1727.22   878.4 1736.28   898.3 1744.68   918.2 1752.24
   928.2 1755.43   938.1 1758.09     968 1763.55   997.8 1770.42  1017.7 1774.52
#Mann= 3 , 0 , 0
       0      .1       0   545.2    .045       0   560.2      .1       0
Bank Sta=545.2,560.2
XS Rating Curve= 0 ,0
Exp/Cntr=0.3,0.1

Type RM Length L Ch R = 1 ,7740.6  ,584.8,590.9,597
XS GIS Cut Line= 4
     1936709.086       348264.46     1936578.849      347948.931
     1936149.151      347502.327     1936066.198      347217.175
#Sta/Elev= 30
       0 1691.36    97.5 1692.27     156 1694.95   253.6 1697.74   292.6 1697.42
   312.1 1695.94   331.6 1692.38   361.3 1684.28   401.3 1671.77   411.3 1670.57
   431.3 1670.38   537.4 1670.39   552.4 1670.52   631.2 1673.02   801.2 1672.66
   871.1 1673.32   881.1  1674.6   891.1  1677.7   901.1 1681.66   931.1 1694.49
   951.1 1704.13   961.1 1709.79   980.9 1714.73  1000.7 1717.86  1020.5 1718.68
    1070 1717.58  1119.5 1717.75  1208.6 1721.19  1238.3  1721.5  1258.1 1720.89
#Mann= 3 , 0 , 0
       0     .06       0   537.4    .045       0   552.4     .06       0
Bank Sta=537.4,552.4
XS Rating Curve= 0 ,0
Exp/Cntr=0.3,0.1

Type RM Length L Ch R = 1 ,7149.6  ,232.2,235.7,238.2
XS GIS Cut Line= 2
     1937114.072      347878.765      1936600.21      346923.382
#Sta/Elev= 30
       0 1694.16      10 1693.06    39.8 1688.16    89.6 1683.79   129.4 1679.06
   189.1 1675.14   258.8 1669.31   308.5 1667.43   338.4 1664.42   348.3 1664.85
   358.3 1665.94   378.2 1669.26   388.1 1670.49   398.1 1670.62     418 1668.31
     428 1667.45   437.9 1667.14   467.8 1666.84   544.8 1666.99   559.8 1667.06
   656.9    1669   756.4 1674.31   816.1 1676.75   875.8 1677.87   905.7 1680.08
   955.4 1685.45   965.4  1686.9   975.3 1689.31    1055  1713.2  1084.8 1723.41
#Mann= 3 , 0 , 0
       0     .06       0   544.8    .045       0   559.8     .06       0
#XS Ineff= 2 , 0
          381.91 1670.53   845.9         1680.27
Permanent Ineff=
       F       F
Bank Sta=544.8,559.8
XS Rating Curve= 0 ,0
Exp/Cntr=0.3,0.1

Type RM Length L Ch R = 1 ,6913.8  ,357.5,353.6,349.5
XS GIS Cut Line= 3
     1937229.273      347730.448     1936987.326      347189.524
     1936864.624      347037.442
#Sta/Elev= 30
       0 1697.74    59.3 1686.85   108.6 1678.73   118.5 1677.21   128.4 1676.12
   138.3 1675.49   148.1 1675.58   167.9  1676.5   197.5 1676.52   207.4 1676.31
   217.3 1675.66   227.2 1674.45   246.9  1671.1   256.8    1670   266.7 1669.61
   414.8 1667.56   548.2 1666.88   553.1 1666.85   563.2 1666.86   572.8 1667.19
   582.7 1668.28   592.6 1670.06   670.7  1685.5   690.3 1689.54   709.8 1694.04
   739.1 1702.65   748.9 1704.78   758.7 1705.84   768.4 1706.14     788 1706.26
#Mann= 3 , 0 , 0
       0     .06       0   548.2    .045       0   563.2     .06       0
Bank Sta=548.2,563.2
XS Rating Curve= 0 ,0
Exp/Cntr=0.3,0.1

Type RM Length L Ch R = 1 ,6559.3  ,252.5,252.3,253.3
XS GIS Cut Line= 3
     1937536.891      347524.793     1937225.816      346970.043
      1937154.96        346838.7
#Sta/Elev= 30
       0 1689.64    49.7 1687.15   198.8 1678.79   208.7 1677.65   218.6 1676.08
   258.4 1668.84   278.3 1666.17   298.1 1664.31     318 1663.69   337.9 1663.95
   397.5 1665.68   421.9 1665.42   436.9 1665.55     487 1665.84   516.8 1667.06
   526.7 1668.03   536.6 1670.08   546.6 1673.15   576.4 1683.36   586.3 1686.12
   616.1 1693.31   626.1 1696.12     636 1699.26   665.9 1709.89   675.8 1713.18
   685.8  1715.9   715.6 1722.61   765.4 1733.34   775.3 1735.39   785.2 1736.94
#Mann= 3 , 0 , 0
       0     .06       0   421.9    .045       0   436.9     .06       0
Bank Sta=421.9,436.9
XS Rating Curve= 0 ,0
Exp/Cntr=0.3,0.1

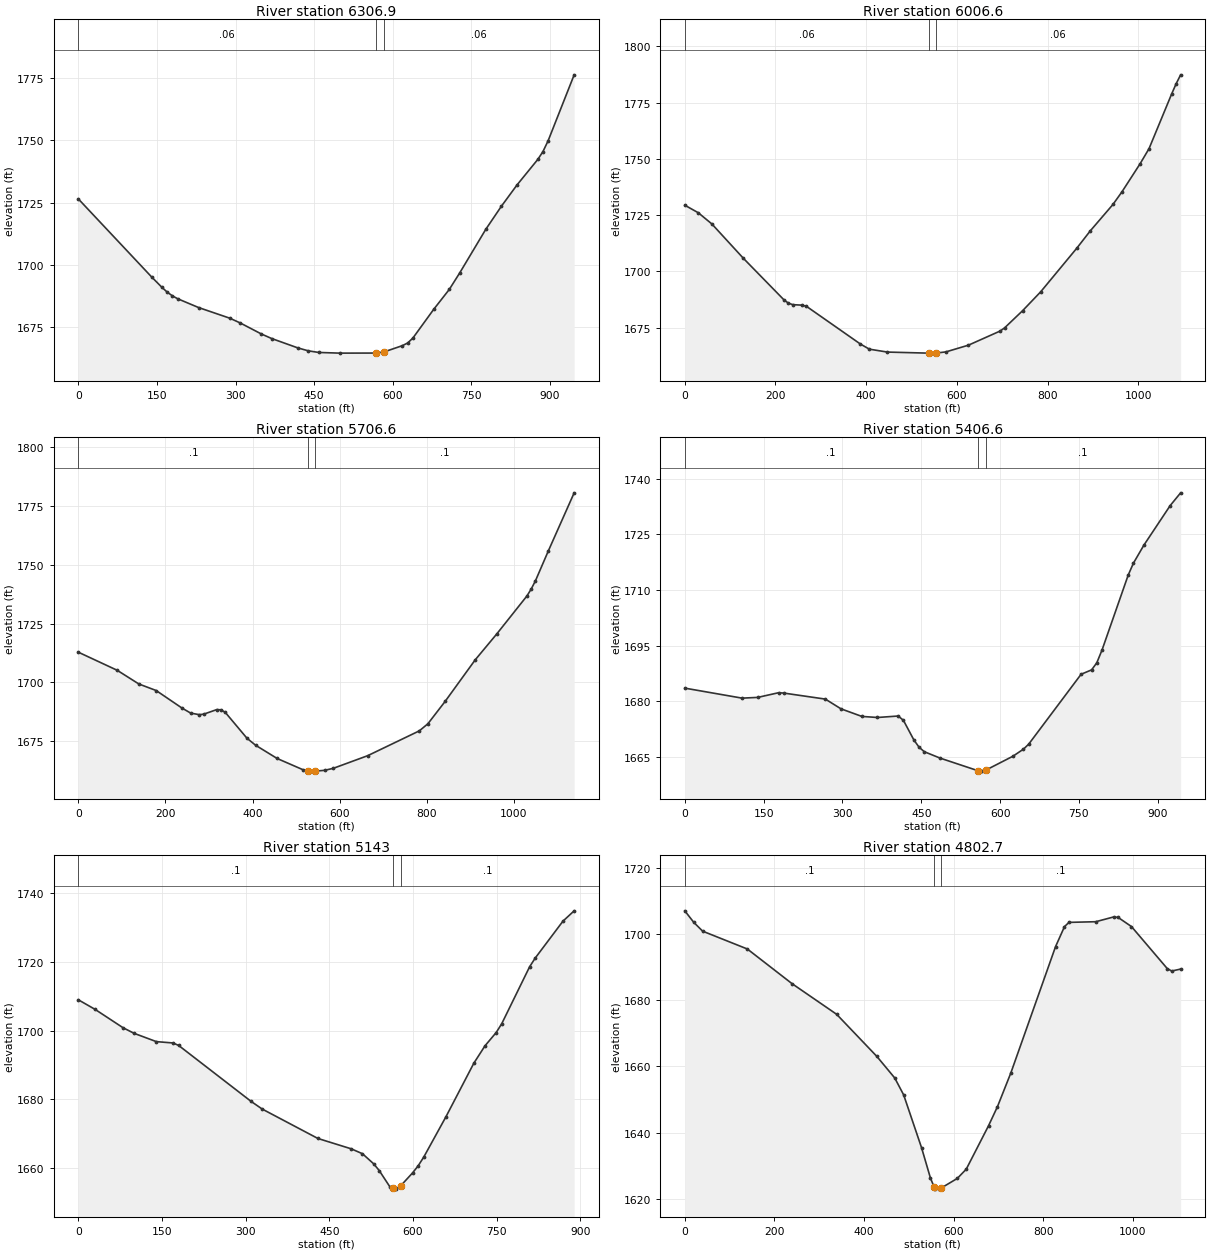
Type RM Length L Ch R = 1 ,6306.9  ,293.4,300.1,308
XS GIS Cut Line= 3
     1937738.505      347521.047     1937431.472      346961.402
     1937293.216      346686.619
#Sta/Elev= 30
       0 1726.49   139.6  1695.2   159.6 1690.95   169.6 1689.05   179.5 1687.56
   189.5  1686.4   229.4 1682.87   289.2 1678.57   309.2 1676.64   349.1 1672.26
     369 1670.41   418.9 1666.65   438.9 1665.47   458.8 1664.83   498.7 1664.56
   567.4 1664.59   582.4 1664.99   618.4 1667.58   628.4 1668.65   638.3 1670.63
     678 1682.16   707.8 1690.18   727.6 1696.78   777.2 1714.25     807 1723.53
   836.8 1732.08   876.5 1742.35   886.4 1745.52   896.3 1749.88   945.9 1776.33
#Mann= 3 , 0 , 0
       0     .06       0   567.4    .045       0   582.4     .06       0
Bank Sta=567.4,582.4
XS Rating Curve= 0 ,0
Exp/Cntr=0.3,0.1

Type RM Length L Ch R = 1 ,6006.6  ,306.3,299.8,292.2
XS GIS Cut Line= 3
     1937862.583       347482.49     1937750.802      346948.143
       1937668.8      346406.855
#Sta/Elev= 30
       0 1729.43    29.8 1726.06    59.6 1721.11     129 1705.86   218.4 1687.41
   228.3  1685.9   238.2 1685.22   258.1 1685.01     268 1684.52   387.1 1667.74
     407 1665.44   446.7 1664.15     536 1663.68   538.4 1663.68   553.4 1663.69
   575.8 1664.23   625.5 1667.22   695.2 1673.48   705.2  1674.9     745 1682.55
   784.8 1690.93   864.4 1710.31   894.3 1718.05   944.1 1729.74     964 1735.36
  1003.8 1747.77  1023.7 1754.55  1073.5 1778.81  1083.4 1783.36  1093.4 1787.37
#Mann= 3 , 0 , 0
       0     .06       0   538.4    .045       0   553.4     .06       0
Bank Sta=538.4,553.4
XS Rating Curve= 0 ,0
Exp/Cntr=0.3,0.1

Type RM Length L Ch R = 1 ,5706.6  ,301.3,299.9,300.3
XS GIS Cut Line= 3
     1938296.986      347394.048     1938046.192      346920.322
     1937765.456      346387.141
#Sta/Elev= 30
       0 1712.84    89.3 1705.13     139  1699.3   178.7 1696.52   238.2 1689.03
   258.1  1686.9   277.9 1686.24   287.9 1686.45   317.6 1688.38   327.6 1688.31
   337.5  1687.2   387.1 1676.24     407 1673.23   456.6 1667.58   516.2 1662.77
   528.5  1662.3   543.5  1662.2   565.6 1662.54   585.4 1663.39   664.4 1668.77
     783 1679.34   802.7 1682.36   842.2 1691.86   911.4 1709.58   960.8 1720.59
  1029.9 1736.72  1039.8 1739.67  1049.7 1743.23  1079.3 1755.96  1138.6 1780.69
#Mann= 3 , 0 , 0
       0      .1       0   528.5    .045       0   543.5      .1       0
Bank Sta=528.5,543.5
XS Rating Curve= 0 ,0
Exp/Cntr=0.3,0.1

Type RM Length L Ch R = 1 ,5406.6  ,268.5,263.4,256.2
XS GIS Cut Line= 3
     1938531.539      347219.988     1938251.763      346729.388
     1938088.185      346387.641
#Sta/Elev= 30
       0 1683.54     109 1680.84   138.7 1681.04   178.4  1682.3   188.3 1682.21
   267.5 1680.58   297.2 1677.96   336.9 1675.91   366.6 1675.62   406.2 1676.02
   416.1 1674.84     436 1669.55   445.9 1667.59   455.8 1666.39   485.5 1664.68
   557.3 1661.29   564.8 1661.15   572.3 1661.38   624.6 1665.18   644.5 1667.08
   654.5 1668.43   754.2 1687.28   774.2 1688.47   784.1 1690.38   794.1 1693.85
   843.9 1714.06   853.9 1717.29   873.8 1722.14   923.7 1732.78   943.6 1736.23
#Mann= 3 , 0 , 0
       0      .1       0   557.3    .045       0   572.3      .1       0
Bank Sta=557.3,572.3
XS Rating Curve= 0 ,0
Exp/Cntr=0.3,0.1

Type RM Length L Ch R = 1 ,5143    ,334.9,340,344.9
XS GIS Cut Line= 2
     1938769.094      346992.509     1938183.236      346323.698
#Sta/Elev= 30
       0 1708.99      30 1706.21    79.9 1700.89    99.9 1699.24   139.9 1696.82
   169.8 1696.43   179.8 1695.72   309.7 1679.44   329.7  1677.2   429.6 1668.64
   489.5 1665.62   509.5  1664.2   529.5 1661.28   539.5 1659.32   559.4 1654.39
   563.5 1654.19   569.4  1653.9   578.5 1654.95   599.4 1658.63   609.4 1660.69
   619.4 1663.22   659.4 1675.02   709.3 1690.57   729.3 1695.62   749.3 1699.47
   759.2 1702.02   809.2 1718.59   819.2 1721.12   869.1 1731.89   889.1 1734.88
#Mann= 3 , 0 , 0
       0      .1       0   563.5    .045       0   578.5      .1       0
Bank Sta=563.5,578.5
XS Rating Curve= 0 ,0
Exp/Cntr=0.3,0.1

Type RM Length L Ch R = 1 ,4802.7  ,201.4,204.7,208.1
XS GIS Cut Line= 2
     1938949.399      346873.821     1938404.867      345909.875
#Sta/Elev= 30
       0 1707.03      20 1703.55    39.9 1700.88   139.6  1695.5   239.4 1685.03
   339.1 1675.76   428.9 1663.03   468.8 1656.52   488.7 1651.41   528.6 1635.47
   548.6 1626.24   556.8 1623.56   558.5 1623.01   568.5 1622.94   571.8 1623.22
   608.4 1626.17   628.4 1628.96   678.2 1642.09   698.2 1647.88   728.1 1658.08
   827.8  1696.2   847.8 1702.26   857.8 1703.54   917.6 1703.74   957.5 1705.18
   967.5 1705.04   997.4 1702.27  1077.2 1689.59  1087.2 1688.84  1107.1 1689.43
#Mann= 3 , 0 , 0
       0      .1       0   556.8    .045       0   571.8      .1       0
Bank Sta=556.8,571.8
XS Rating Curve= 0 ,0
Exp/Cntr=0.3,0.1

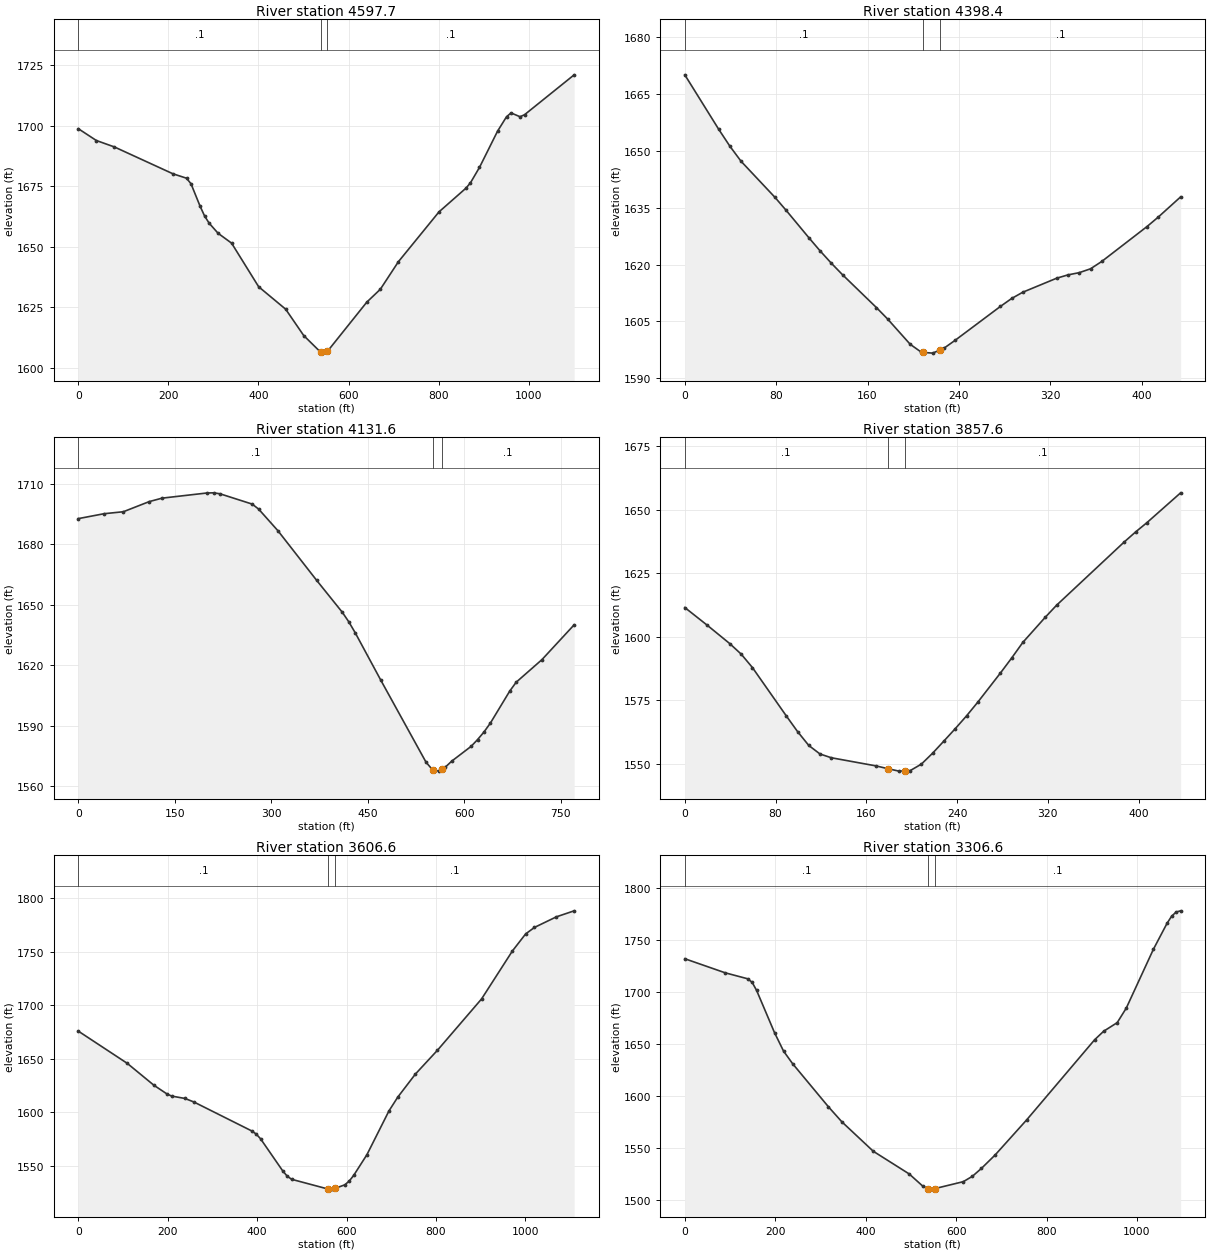
Type RM Length L Ch R = 1 ,4597.7  ,199.6,199.2,198.8
XS GIS Cut Line= 2
     1939062.405       346835.16     1938669.276      345806.712
#Sta/Elev= 30
       0 1698.69      40 1693.82    80.1 1691.16   210.2 1680.08   240.2 1678.27
   250.2 1675.97   270.2 1666.79   280.3 1662.71   290.3 1659.76   310.3 1655.56
   340.3 1651.49   400.4  1633.5   460.4 1624.24   500.5 1613.37   538.1  1606.5
   540.5 1606.12   553.1 1606.84   640.6 1627.16   670.6 1632.46   710.7 1643.82
   800.8 1664.37   860.8 1674.17   870.8 1676.39   890.8 1682.74   930.9 1697.67
   950.9 1703.64   960.9 1705.19   980.9 1703.62   990.9 1704.46    1101 1720.91
#Mann= 3 , 0 , 0
       0      .1       0   538.1    .045       0   553.1      .1       0
Bank Sta=538.1,553.1
XS Rating Curve= 0 ,0
Exp/Cntr=0.3,0.1

Type RM Length L Ch R = 1 ,4398.4  ,279,266.6,254.2
XS GIS Cut Line= 2
     1939140.656      346474.051     1938978.205      346071.382
#Sta/Elev= 30
       0 1670.09    29.6 1655.76    39.5 1651.24    49.3 1647.26      79 1637.74
    88.8  1634.3   108.6 1627.11   118.4 1623.65   128.3 1620.37   138.2  1617.3
   167.8 1608.66   177.6 1605.64   197.4 1598.96   207.2 1596.86   208.5 1596.83
   217.1 1596.63   223.5 1597.47     227 1597.93   236.8 1600.03   276.3 1608.94
   286.2 1611.05     296 1612.71   325.6  1616.4   335.5 1617.28   345.4 1617.87
   355.3 1618.89   365.1 1620.82   404.6    1630   414.5 1632.51   434.2 1637.87
#Mann= 3 , 0 , 0
       0      .1       0   208.5    .045       0   223.5      .1       0
Bank Sta=208.5,223.5
XS Rating Curve= 0 ,0
Exp/Cntr=0.3,0.1

Type RM Length L Ch R = 1 ,4131.6  ,260.9,274.1,286.9
XS GIS Cut Line= 2
      1939667.17      346413.367      1939049.31       345952.94
#Sta/Elev= 30
       0 1692.72      40 1695.15      70 1696.13   110.1 1701.15   130.1 1702.87
   200.1 1705.44   210.2 1705.51   220.2 1705.03   270.2 1699.92   280.2 1697.45
   310.2 1686.71   370.3 1662.14   410.3 1646.25   420.3 1641.55   430.3 1636.11
   470.3 1612.46   540.4 1571.89   550.5 1568.14   560.4 1567.47   565.5 1568.48
   570.4 1569.45   580.4 1572.44   610.4 1579.74   620.4 1583.08   630.4 1586.86
   640.4  1591.3   670.5 1607.18   680.5 1611.57   720.5 1622.76   770.6 1640.05
#Mann= 3 , 0 , 0
       0      .1       0   550.5    .045       0   565.5      .1       0
Bank Sta=550.5,565.5
XS Rating Curve= 0 ,0
Exp/Cntr=0.3,0.1

Type RM Length L Ch R = 1 ,3857.6  ,250.8,251.1,254
XS GIS Cut Line= 2
     1939448.274       346035.09     1939291.009      345627.236
#Sta/Elev= 30
       0 1611.51    19.9 1604.49    39.7 1597.28    49.7 1593.17    59.6 1587.89
    89.4  1568.9    99.4 1562.69   109.3 1557.22   119.2 1553.86   129.2 1552.38
   168.9 1549.15   178.8  1548.1   188.8 1547.12   193.8 1547.22   198.7 1547.32
   208.6 1549.89   218.6 1554.24   228.5    1559   238.4 1563.82   248.4 1568.88
   258.3 1574.27   278.2  1585.7   288.1  1591.6     298 1597.78   317.9 1607.73
   327.8 1612.43   387.4 1637.31   397.4 1641.24   407.3 1644.87   437.1 1656.64
#Mann= 3 , 0 , 0
       0      .1       0   178.8    .045       0   193.8      .1       0
Bank Sta=178.8,193.8
XS Rating Curve= 0 ,0
Exp/Cntr=0.3,0.1

Type RM Length L Ch R = 1 ,3606.6  ,300.1,299.8,299.4
XS GIS Cut Line= 3
     1939798.975      346305.403      1939613.16      345770.108
     1939491.206      345241.637
#Sta/Elev= 30
       0 1675.82   109.4 1645.73     169 1625.26   198.8 1616.95   208.8 1615.12
   238.6 1612.88   258.5 1609.59   387.7 1582.57   397.6 1579.69   407.6  1575.2
   457.3 1545.11   467.2 1540.23   477.2  1537.3   559.1 1528.15   566.6 1528.13
   574.1 1528.79   596.2 1532.18   606.1 1535.77   615.9 1540.99   645.5 1560.34
   694.8 1601.27   714.5 1614.15     754 1635.74   803.3 1657.98   901.9 1705.93
   970.9 1750.78  1000.5 1766.72  1020.2 1772.78  1069.5 1782.73    1109  1788.3
#Mann= 3 , 0 , 0
       0      .1       0   559.1    .045       0   574.1      .1       0
Bank Sta=559.1,574.1
XS Rating Curve= 0 ,0
Exp/Cntr=0.3,0.1

Type RM Length L Ch R = 1 ,3306.6  ,302.3,299.9,294.7
XS GIS Cut Line= 3
     1940094.389       346247.16     1939908.886      345733.682
     1939771.565      345200.478
#Sta/Elev= 30
       0 1732.34    89.3  1718.8     139 1713.06   148.9 1709.67   158.8 1701.87
   198.5 1661.17   218.4  1643.5   238.2 1631.52   317.6 1589.94   347.4 1575.44
   416.9 1547.12   496.3 1525.31   526.1 1513.68   538.5 1510.96     546 1510.71
   553.5 1511.26     616  1517.9   636.1 1523.07   656.1 1530.67   686.1 1543.45
   756.2 1577.37   906.4 1654.39   926.4  1662.6   956.4 1670.88   976.4 1684.85
  1036.5 1741.54  1066.5 1766.35  1076.5 1773.12  1086.6 1777.27  1096.6 1778.42
#Mann= 3 , 0 , 0
       0      .1       0   538.5    .045       0   553.5      .1       0
Bank Sta=538.5,553.5
XS Rating Curve= 0 ,0
Exp/Cntr=0.3,0.1

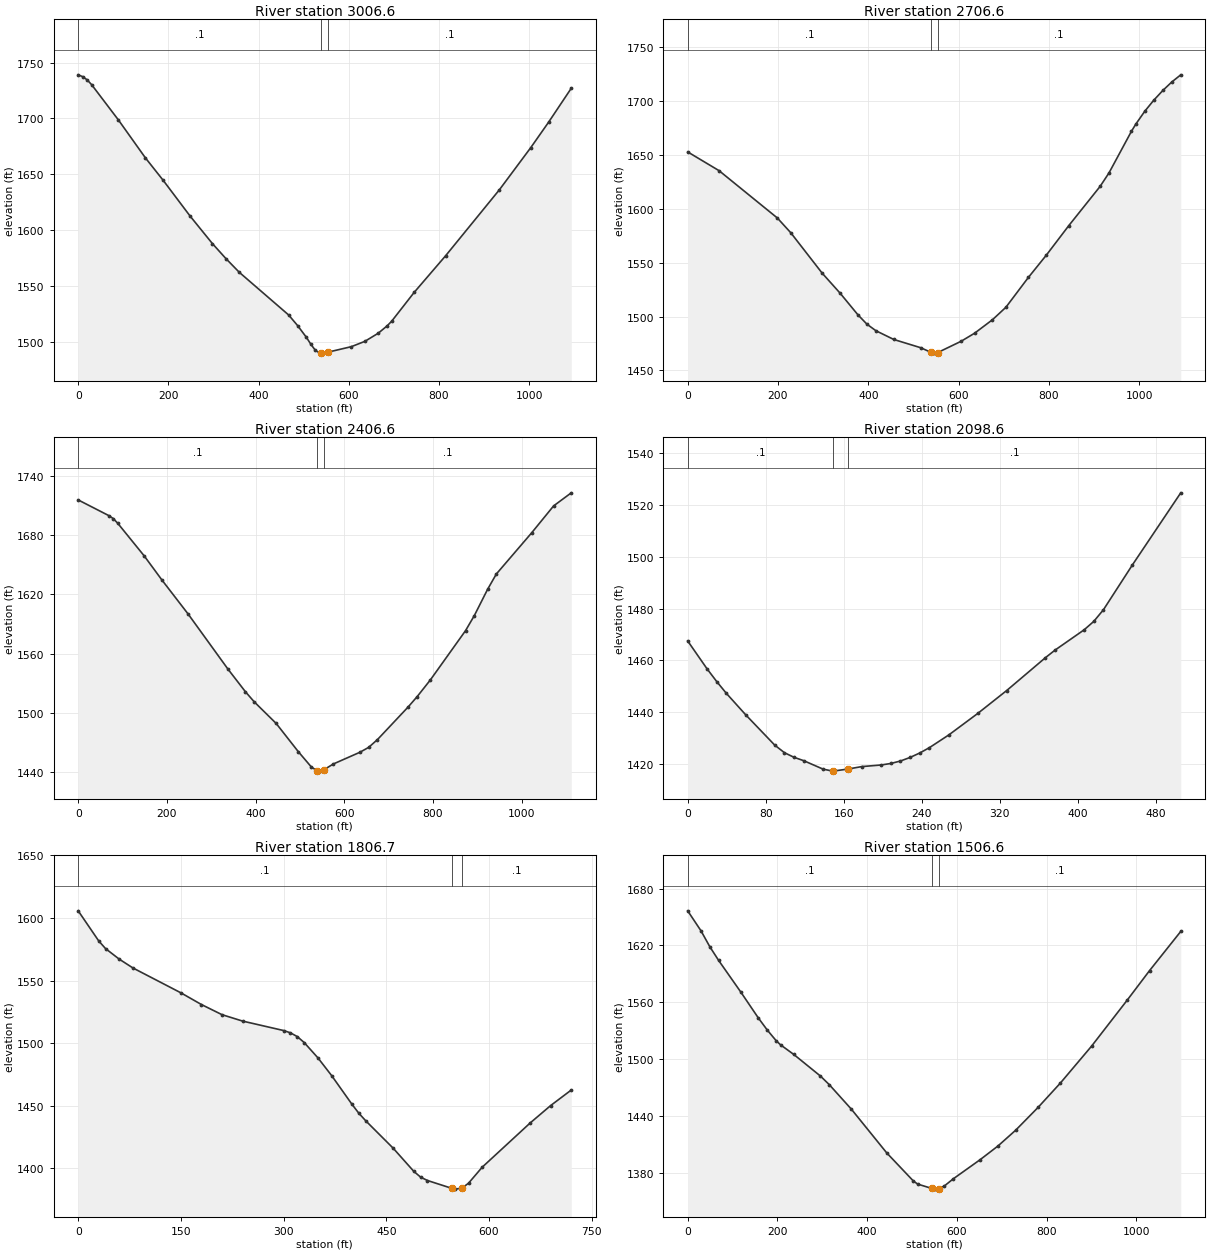
Type RM Length L Ch R = 1 ,3006.6  ,302.2,300,298.5
XS GIS Cut Line= 3
     1940424.222      346111.452     1940185.451      345620.637
     1939931.266       345135.99
#Sta/Elev= 30
       0 1739.03     9.9 1737.39    19.8 1734.54    29.8 1730.21    89.3 1698.53
   148.9 1664.71   188.6 1644.43   248.1  1612.5   297.7 1587.79   327.5 1574.44
   357.3 1562.08   466.4 1523.99   486.3 1514.49   506.1  1503.8     516 1497.56
     526 1492.16   535.9 1489.76   538.3 1489.76   553.3 1490.58   605.5 1495.55
   635.4 1500.28   665.2  1507.6   685.1 1514.25   695.1 1518.41   744.8 1544.15
   814.5 1576.94   933.9 1636.14  1003.5 1673.93  1043.3 1696.87  1093.1    1727
#Mann= 3 , 0 , 0
       0      .1       0   538.3    .045       0   553.3      .1       0
Bank Sta=538.3,553.3
XS Rating Curve= 0 ,0
Exp/Cntr=0.3,0.1

Type RM Length L Ch R = 1 ,2706.6  ,306.8,300,292.6
XS GIS Cut Line= 3
     1940722.963      345926.398     1940437.659      345460.897
     1940152.974      344994.828
#Sta/Elev= 30
       0 1652.81    69.5 1635.41   198.5 1591.53   228.3 1577.82   297.8 1540.33
   337.5 1521.77   377.2 1501.57   397.1 1492.92   416.9 1486.88   456.6 1478.74
   516.2  1471.1   538.5 1466.88     546 1466.09   553.5 1466.56   605.6 1477.09
   635.3 1484.53   675.1 1497.09   704.8 1508.65   754.5 1536.29   794.2 1556.93
   843.9 1584.31   913.4 1620.78   933.2 1633.37   982.9 1671.98   992.8 1678.78
  1012.7 1690.72  1032.5 1700.88  1052.4 1709.84  1072.2 1717.69  1092.1 1724.35
#Mann= 3 , 0 , 0
       0      .1       0   538.5    .045       0   553.5      .1       0
Bank Sta=538.5,553.5
XS Rating Curve= 0 ,0
Exp/Cntr=0.3,0.1

Type RM Length L Ch R = 1 ,2406.6  ,293.3,307.6,322.5
XS GIS Cut Line= 3
     1941088.986      345648.271     1940678.774      345288.554
     1940243.675      344926.433
#Sta/Elev= 30
       0 1715.88    69.4 1699.89    79.4 1696.82    89.3 1692.12   148.8 1659.09
   188.5 1634.78     248    1600   337.3 1544.39     377 1521.23   396.8    1511
   446.4 1489.02     496 1460.53   525.8 1444.76   538.1 1441.17   545.6 1440.62
   553.1 1441.78   575.4  1447.9     635 1459.74   654.8 1464.69   674.7 1472.61
   744.2 1505.87   764.1 1516.17   793.9 1533.12   873.3 1583.18   893.2 1598.54
     923  1625.1   942.8 1640.71  1022.3 1682.43  1071.9 1709.81  1111.7 1723.09
#Mann= 3 , 0 , 0
       0      .1       0   538.1    .045       0   553.1      .1       0
Bank Sta=538.1,553.1
XS Rating Curve= 0 ,0
Exp/Cntr=0.3,0.1

Type RM Length L Ch R = 1 ,2098.6  ,309.2,291.6,274
XS GIS Cut Line= 2
     1940924.152      345245.305     1940817.004      344751.041
#Sta/Elev= 30
       0 1467.47    19.8 1456.72    29.8 1451.76    39.7  1447.2    59.5 1438.92
    89.2 1427.23    99.2 1424.28   109.1 1422.48     119 1421.19   138.8 1417.93
   148.8 1417.15   149.3 1417.17   164.3 1417.95   178.5  1418.9   198.3 1419.52
   208.2  1420.1   218.2 1421.06   228.1 1422.44     238 1424.16   247.9 1426.22
   267.8 1431.14   297.5 1439.45   327.2 1448.31   366.9    1461   376.8 1463.94
   406.6 1471.77   416.5 1475.03   426.4 1479.53   456.2 1496.91   505.7 1524.72
#Mann= 3 , 0 , 0
       0      .1       0   149.3    .045       0   164.3      .1       0
Bank Sta=149.3,164.3
XS Rating Curve= 0 ,0
Exp/Cntr=0.3,0.1

Type RM Length L Ch R = 1 ,1806.7  ,291.9,300.1,309.7
XS GIS Cut Line= 2
      1941570.62       345238.61     1940965.629       344847.82
#Sta/Elev= 30
       0 1605.69      30 1581.62      40 1575.49      60 1567.06      80 1560.02
     150 1540.17   180.1 1530.79   210.1  1522.7   240.1 1517.59   300.1 1510.03
   310.1 1508.19   320.1 1505.15   330.1 1500.44   350.1 1488.24   370.1  1474.1
   400.1 1450.94   410.1 1443.83   420.1 1437.86   460.2 1415.95   490.2 1397.52
   500.2 1392.87   510.2  1390.2   545.5 1383.98   550.2 1383.31   560.5 1384.08
   570.2 1388.08   590.2 1400.88   660.2 1436.19   690.2 1450.13   720.2  1462.5
#Mann= 3 , 0 , 0
       0      .1       0   545.5    .045       0   560.5      .1       0
Bank Sta=545.5,560.5
XS Rating Curve= 0 ,0
Exp/Cntr=0.3,0.1

Type RM Length L Ch R = 1 ,1506.6  ,194.7,192.2,188.1
XS GIS Cut Line= 3
      1941632.52       345179.72     1941304.315      344735.797
     1941010.304      344274.696
#Sta/Elev= 30
       0 1656.45    29.6 1635.37    49.3 1618.54      69 1604.04   118.3 1570.71
   157.7 1543.12   177.4  1530.5   197.2 1519.26     207  1514.9   236.6  1504.7
   295.8 1481.95   315.5 1472.88   364.8 1446.95   443.6 1400.77   502.8 1371.17
   512.6 1367.79   544.6 1363.17   552.1  1362.5   559.6 1363.02     572 1365.82
   591.8 1373.35   651.5 1393.51   691.3 1407.98     731 1424.75   780.8 1448.77
   830.5 1474.48   900.1 1513.51   979.6 1562.15  1029.3 1593.28  1098.9 1634.69
#Mann= 3 , 0 , 0
       0      .1       0   544.6    .045       0   559.6      .1       0
Bank Sta=544.6,559.6
XS Rating Curve= 0 ,0
Exp/Cntr=0.3,0.1