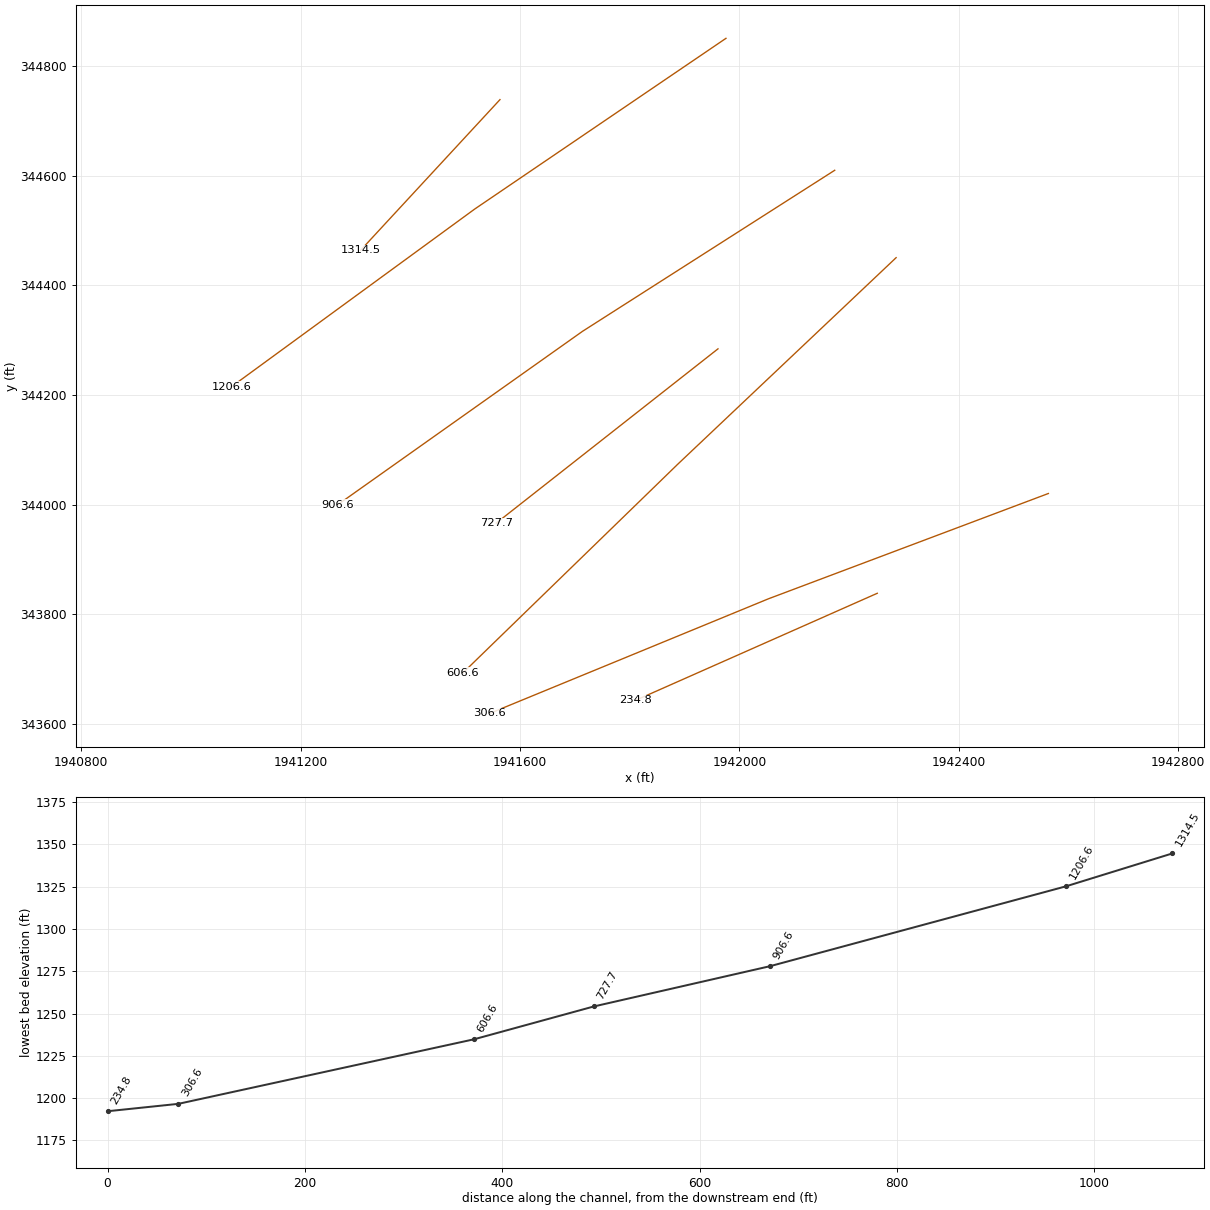
HEC-RAS study MeadowFork.prj: MeadowFork

--- MeadowFork.g01 (geometry) --- (continued)

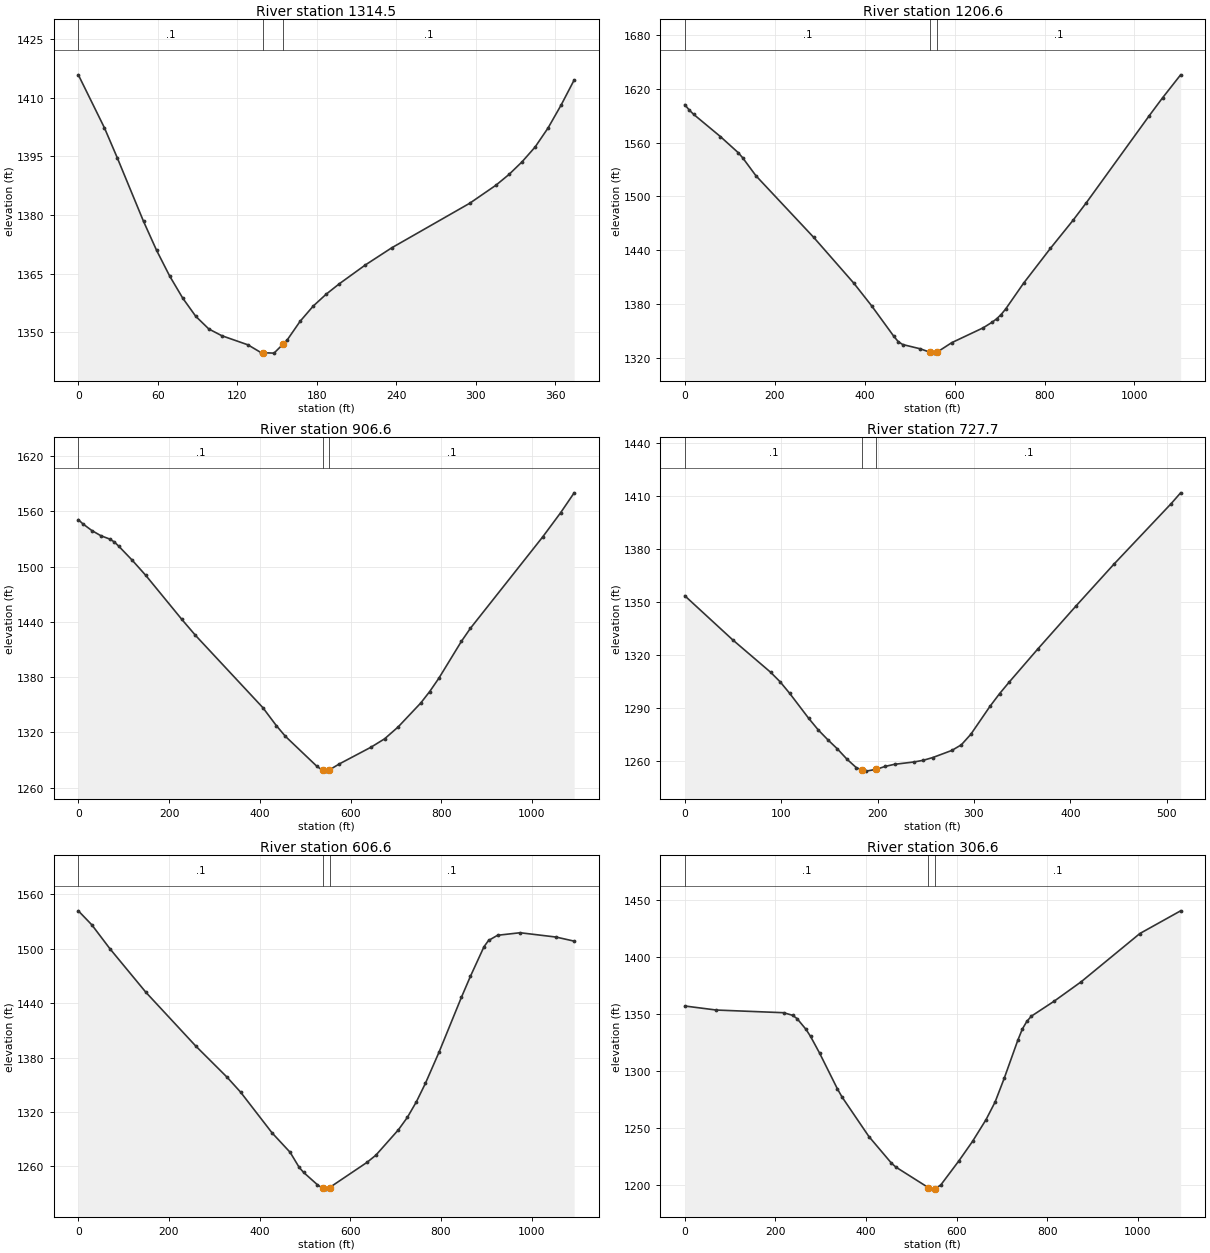
Type RM Length L Ch R = 1 ,1314.5  ,112.8,107.8,103.5
XS GIS Cut Line= 2
     1941563.584      344738.944      1941309.54      344464.161
#Sta/Elev= 30
       0 1415.83    19.7 1402.28    29.5 1394.53    49.2 1378.37    59.1 1370.93
    68.9 1364.41    78.8 1358.74    88.6  1354.1    98.5 1350.85   108.3 1349.13
     128  1346.8   137.9 1344.81   139.3 1344.79   147.7 1344.68   154.3 1346.91
   157.6 1348.03   167.4 1352.83   177.3 1356.72   187.1 1359.76     197 1362.42
   216.7 1367.24   236.4 1371.58   295.4    1383   315.1 1387.59     325 1390.35
   334.8 1393.56   344.7 1397.36   354.5 1402.24   364.4 1408.13   374.2 1414.51
#Mann= 3 , 0 , 0
       0      .1       0   139.3    .045       0   154.3      .1       0
Bank Sta=139.3,154.3
XS Rating Curve= 0 ,0
Exp/Cntr=0.3,0.1

Type RM Length L Ch R = 1 ,1206.6  ,300.6,300,299.6
XS GIS Cut Line= 3
     1941975.588      344850.758     1941517.605      344539.425
     1941074.465       344215.56
#Sta/Elev= 30
       0 1602.27     9.9 1596.32    19.8 1591.46    79.1 1566.76   118.7 1548.83
   128.6 1543.15   158.2 1523.04   286.8 1454.26   375.8 1403.31   415.3 1378.14
   464.8 1344.05   474.7 1338.06   484.6 1334.82   524.1    1330   546.3 1326.04
   553.8 1325.24   561.3 1326.38   593.7 1336.91   663.6 1353.46   683.5 1359.73
   693.5 1363.48   703.5  1368.3   713.5 1374.37   753.4 1403.18   813.2 1442.12
   863.2 1473.21   893.1 1493.03  1032.8 1589.93  1062.7 1610.06  1102.7 1635.58
#Mann= 3 , 0 , 0
       0      .1       0   546.3    .045       0   561.3      .1       0
Bank Sta=546.3,561.3
XS Rating Curve= 0 ,0
Exp/Cntr=0.3,0.1

Type RM Length L Ch R = 1 ,906.6   ,176.5,178.8,180
XS GIS Cut Line= 3
     1942173.831       344610.09     1941713.871      344316.229
     1941267.422       343999.82
#Sta/Elev= 30
       0 1550.99     9.9 1546.44    29.8 1539.14    49.6 1533.54    69.5 1529.83
    79.4 1526.72    89.3 1522.06   119.1 1506.78   148.9 1490.35   228.2 1442.68
     258 1425.51   406.9 1346.85   436.6 1327.34   456.5 1315.79     526 1283.21
   538.3    1279   545.8 1278.03   553.3 1279.37   575.7 1285.94   645.3 1304.04
   675.2 1313.11     705 1325.99   754.8 1351.95   774.6 1364.44   794.6 1378.75
   844.3 1418.78   864.2 1432.98  1023.4 1532.07  1063.2  1558.5    1093 1580.07
#Mann= 3 , 0 , 0
       0      .1       0   538.3    .045       0   553.3      .1       0
Bank Sta=538.3,553.3
XS Rating Curve= 0 ,0
Exp/Cntr=0.3,0.1

Type RM Length L Ch R = 1 ,727.7   ,119.1,121.1,123.4
XS GIS Cut Line= 2
     1941961.069      344284.429     1941556.672      343966.441
#Sta/Elev= 30
       0 1353.63    49.5 1328.73      89 1310.28    98.9 1304.85   108.8 1298.31
   128.6 1284.09   138.5 1277.53   148.4 1271.98   158.3 1266.81   168.2    1261
   178.1 1256.09   183.7 1255.02     188  1254.2   198.7 1255.21   207.8 1256.87
   217.6 1258.07   237.4 1259.36   247.3 1260.33   257.2 1261.89     277 1265.93
   286.9 1269.12   296.8 1275.13   316.6 1290.92   326.5 1298.09   336.4 1304.58
     366 1323.31   405.6 1347.69   445.2 1371.54   504.6 1405.88   514.4 1411.99
#Mann= 3 , 0 , 0
       0      .1       0   183.7    .045       0   198.7      .1       0
Bank Sta=183.7,198.7
XS Rating Curve= 0 ,0
Exp/Cntr=0.3,0.1

Type RM Length L Ch R = 1 ,606.6   ,309,300,291.3
XS GIS Cut Line= 3
      1942285.79      344450.706     1941888.584      344074.838
     1941496.313      343693.631
#Sta/Elev= 30
       0 1541.98    29.8 1526.49    69.6  1500.2   149.1 1452.04   258.5 1393.05
   328.1 1358.38   357.9 1341.92   427.5 1296.85   467.3 1275.44   487.2 1258.84
   497.1 1253.22     527 1239.87   539.4  1235.6   546.8 1234.84   554.4 1236.62
   636.4 1264.23   656.2  1272.2     706 1300.27   725.9 1314.04   745.8 1331.28
   765.6 1351.53   795.5 1385.73   845.2 1446.67   865.1 1469.88   894.9 1502.37
   904.9 1509.25   924.8 1514.99   974.5  1517.8  1054.1 1513.02  1093.8 1508.52
#Mann= 3 , 0 , 0
       0      .1       0   539.4    .045       0   554.4      .1       0
Bank Sta=539.4,554.4
XS Rating Curve= 0 ,0
Exp/Cntr=0.3,0.1

Type RM Length L Ch R = 1 ,306.6   ,70.4,71.6,72.3
XS GIS Cut Line= 3
      1942563.35      344020.572     1942053.087      343828.523
     1941545.112      343619.517
#Sta/Elev= 30
       0 1357.27    69.4 1353.73   218.1 1351.38   237.9 1349.11   247.8 1346.22
   267.6 1336.76   277.6 1330.58   297.4 1316.05     337 1284.49     347 1277.51
   406.4 1242.78     456 1219.51   465.9 1215.99   537.7 1197.96   545.2 1196.65
   552.7 1196.88   565.2 1200.37   605.1 1221.48   635.1  1238.5     665 1257.63
     685 1273.09     705 1293.77     735 1327.11     745 1336.98   754.9 1343.69
   764.9 1348.32   814.9 1361.37   874.8 1378.46  1004.6 1420.85  1094.5 1440.74
#Mann= 3 , 0 , 0
       0      .1       0   537.7    .045       0   552.7      .1       0
Bank Sta=537.7,552.7
XS Rating Curve= 0 ,0
Exp/Cntr=0.3,0.1

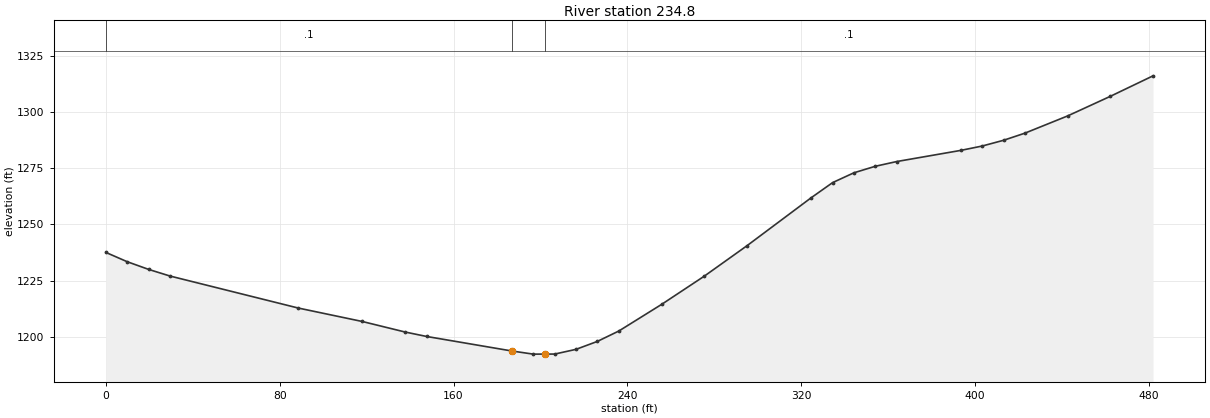
Type RM Length L Ch R = 1 ,234.8   ,238.6,234.9,231.2
XS GIS Cut Line= 2
     1942251.406      343838.555     1941810.716      343643.269
#Sta/Elev= 30
       0 1237.53     9.8  1233.4    19.7 1229.97    29.5 1227.03    88.5  1212.8
     118 1206.81   137.7 1202.13   147.6 1200.15   186.9 1193.68   196.7 1192.29
   201.9 1192.31   206.6 1192.32   216.4 1194.42   226.2 1197.94   236.1 1202.57
   255.8 1214.42   275.4 1226.95   295.1 1240.52   324.6 1261.83   334.5 1268.59
   344.3 1272.95   354.1 1275.84     364 1277.96   393.5 1282.92   403.3 1284.85
   413.2 1287.42     423 1290.58   442.7 1298.26   462.4    1307     482 1316.09
#Mann= 3 , 0 , 0
       0      .1       0   186.9    .045       0   201.9      .1       0
Bank Sta=186.9,201.9
XS Rating Curve= 0 ,0
Exp/Cntr=0.3,0.1

Chan Stop Cuts=-1
Use User Specified Reach Order=0
Composite Channel Slope=5